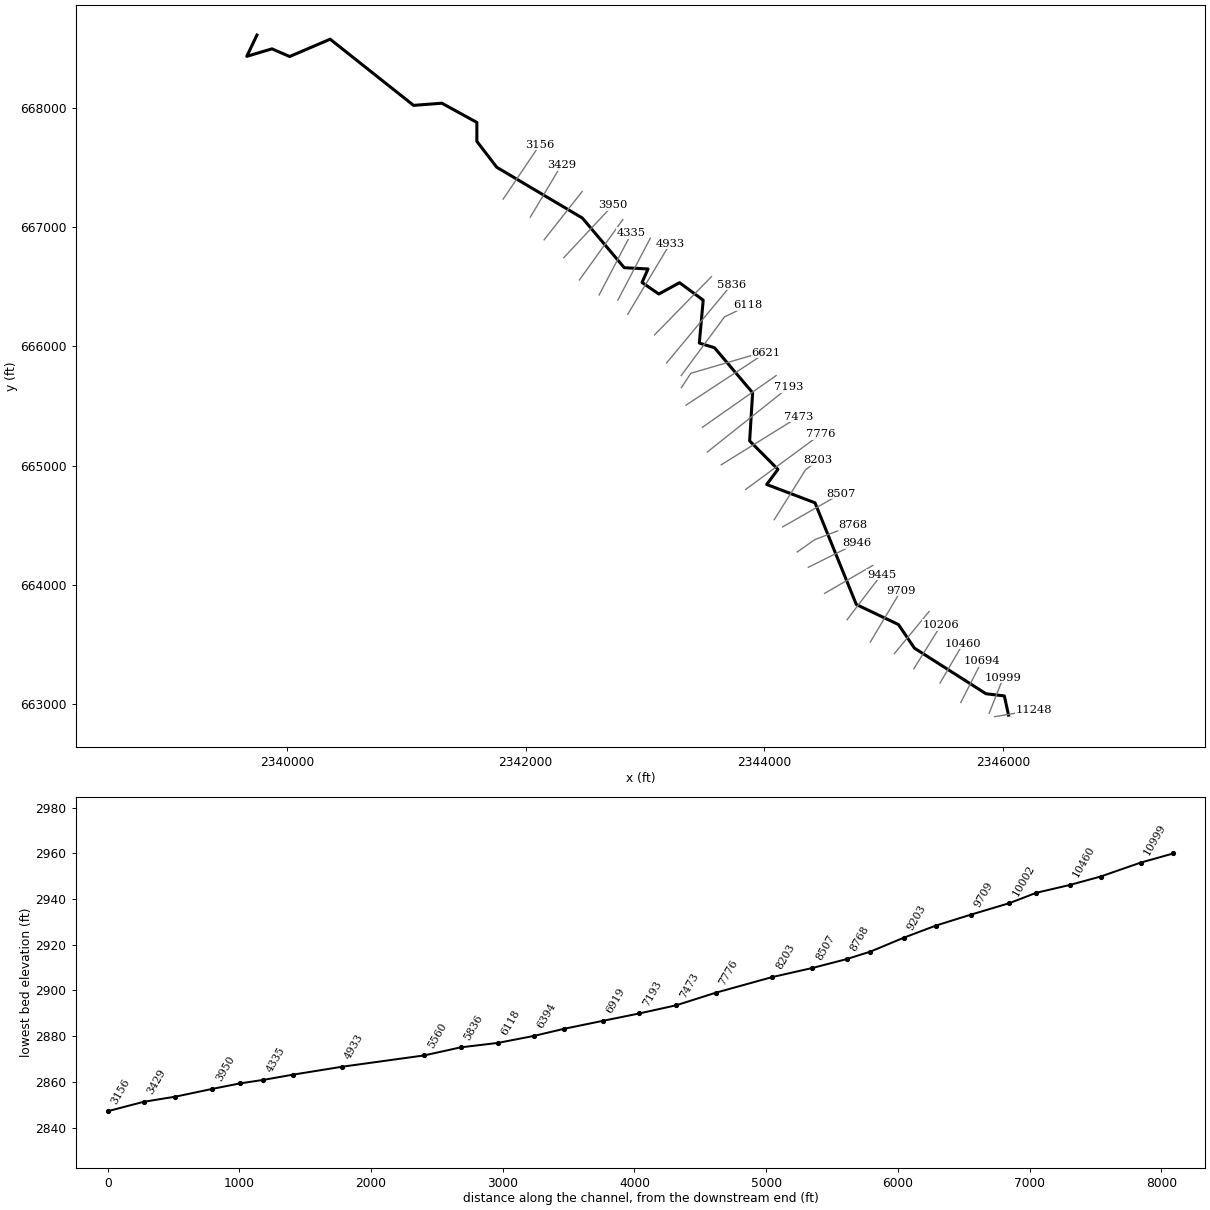
--- DANIELSCK.prj (project) ---

Proj Title=DANIELSCK
Current Plan=p01
Default Exp/Contr=0,0
English Units
Geom File=g01
Flow File=f01
Plan File=p01
BEGIN DESCRIPTION:
----------MODEL BY WOOD PLC 2022----------
AFH study
Randolph County, WV
HEC-RAS Version: RAS 6.2
Vertical Datum: NAVD88
Projection: NAD 1983 StatePlane West Virginia S FIPS 4702 (US Feet)
Terrain: 1-meter LIDAR (FEMA Region III 3DEP collected 2016-2018)
Land Use: 2019 NLCD
Hydrologic Method:
WV SIR2010-5033 regression equations
Additional Model Notes:
None
END DESCRIPTION:
DSS Export Rating Curves= 0
DSS Export Rating Curve Sorted= 0
DSS Export Volume Flow Curves= 0
DXF OffsetX= 0
DXF OffsetY= 0
DXF ScaleX= 0
DXF ScaleY= 0

--- DANIELSCK.p01 (plan) ---

Plan Title=Floodplain
Program Version=6.20
Short Identifier=Floodplain
Geom File=g01
Flow File=f01
Subcritical Flow
K Sum by GR= 0
Std Step Tol= 0.01
Critical Tol= 0.01
Num of Std Step Trials= 20
Max Error Tol= 0.3
Flow Tol Ratio= 0.001
Split Flow NTrial= 30
Split Flow Tol= 0.02
Split Flow Ratio= 0.02
Log Output Level= 0
Friction Slope Method= 1
Unsteady Friction Slope Method= 2
Unsteady Bridges Friction Slope Method= 1
Parabolic Critical Depth
Global Vel Dist= 0 , 0 , 0
Global Log Level= 0
CheckData=True
Encroach Param=-1 ,0,0, 0
Mapping Interval=1HOUR
Computation Time Step Use Courant=        0
Computation Time Step Use Time Series=    0
Computation Time Step Count To Double=0
Computation Time Step Max Doubling=0
Computation Time Step Max Halving=0
Computation Time Step Residence Courant=0
Run HTab= 0
Run UNet= 0
Run Sediment= 0
Run PostProcess= 0
Run WQNet= 0
Run RASMapper=-1
UNET Theta= 0
UNET Theta Warmup= 0
UNET ZTol= 0
UNET ZSATol= 0
UNET MxIter= 0
UNET Max Iter WO Improvement= 0
UNET MaxInSteps= 0
UNET DtIC= 0
UNET DtMin= 0
UNET MaxCRTS= 0
UNET WFStab= 0
UNET SFStab= 0
UNET WFX= 1
UNET SFX= 1
UNET Gravity=32.174
UNET 1D Methodology=Finite Difference
UNET DSS MLevel= 1
UNET Pardiso=0
UNET DZMax Abort= 0
UNET Use Existing IB Tables= 0
UNET Froude Reduction=False
UNET Froude Limit= 0
UNET Froude Power= 0
UNET D1 Cores= 0
UNET WindReference=Eulerian
UNET WindDragFormulation=Hsu (1988)
UNET D2 Coriolis=0
UNET D2 Cores= 0
UNET D2 Theta= 1
UNET D2 Theta Warmup= 1
UNET D2 Z Tol= 0.01
UNET D2 Volume Tol= 0.01
UNET D2 Max Iterations= 20
UNET D2 Equation= 0
UNET D2 RampUpFraction=0.1
UNET D2 TimeSlices= 1
UNET D2 Turbulence Formulation=Non-Conservative (original)
UNET D2 Eddy Viscosity=0.3
UNET D2 Transverse Eddy Viscosity=0.1
UNET D2 Smagorinsky Mixing=0
UNET D2 BCVolumeCheck=0
UNET D2 Cores=0
UNET D2 SolverType=PARDISO (Direct)
UNET D2 Minimum Iterations= 2147483647
UNET D2 Maximum Iterations= 2147483647
UNET D2 Restart Number= 10
UNET D2 Relaxation Coeff=1.3
UNET D2 SOR Precondition Iterations= 10
UNET D2 ILUT Maximum Fill= 8
UNET D2 ILUT Tolerance=1E-08
UNET D1D2 MaxIter= 0
UNET D1D2 ZTol=0.01
UNET D1D2 QTol=0.1
UNET D1D2 MinQTol=1
Write IC File= 0
Write IC File at Fixed DateTime=0
Write IC File at Sim End=0
Echo Input=False
Echo Parameters=False
Echo Output=False
Write Detailed= 0
HDF Write Warmup=0
HDF Write Time Slices=0
HDF Flush=0
HDF Compression= 1
HDF Chunk Size= 1
HDF Spatial Parts= 1
HDF Use Max Rows=0
HDF Fixed Rows= 1
Calibration Method= 0
Calibration Iterations= 20
Calibration Max Change=0.05
Calibration Tolerance=0.2
Calibration Maximum=1.5
Calibration Minimum=0.5
Calibration Optimization Method= 1
WQ AD Non Conservative
WQ ULTIMATE=-1
WQ Max Comp Step=1HOUR
WQ Output Interval=15MIN
WQ Output Selected Increments= 0
WQ Output face flow=0
WQ Output face velocity=0
WQ Output face area=0
WQ Output face dispersion=0
WQ Output cell volume=0
WQ Output cell surface area=0
WQ Output cell continuity=0
WQ Output cumulative cell continuity=0
WQ Output face conc=0
WQ Output face dconc_dx=0
WQ Output face courant=0
WQ Output face peclet=0
WQ Output face adv mass=0
WQ Output face disp mass=0
WQ Output cell mass=0
WQ Output cell source sink temp=0
WQ Output nsm pathways=0
WQ Output nsm derived pathways=0
WQ Create Restart=0
WQ Fixed Restart=0
WQ System Summary=0
WQ Write To DSS=0
Sorting and Armoring Iterations= 10
XS Update Threshold= 0.02
Bed Roughness Predictor= 0
Hydraulics Update Threshold= 0.02
Energy Slope Method= 1
Volume Change Method= 1
Sediment Retention Method= 0
Sediment TS Multiplier= 1
Warm Up Method= 0
XS Weighting Method= 0
Number of US Weighted Cross Sections= 1
Number of DS Weighted Cross Sections= 1
Upstream XS Weight=0
Main XS Weight=1
Downstream XS Weight=0
Number of DS XS's Weighted with US Boundary= 1
Upstream Boundary Weight= 1
Weight of XSs Associated with US Boundary= 0
Number of US XS's Weighted with DS Boundary= 1
Downstream Boundary Weight= 0.5
Weight of XSs Associated with DS Boundary= 0.5
Percentile Method= 0
Sediment Output Level= 3
Mass or Volume Output= 0
Output Increment Type= 1
Profile and TS Output Increment= 1
Transport Output Increment 1
XS Output Flag= 0
XS Output Increment= 10
Read HDF5 Sediment Hotstart= 0
Sediment Hotstart Type= 0
Write Gradation File= 0
Read Gradation Hotstart= 0
Write HDF5 File= 1
Write Binary Output= 1
Write DSS Sediment File= 0
DSS Sediment Output Type= 1
SV Curve= 0
Specific Gage Flag= 0
Subcell Erosion Methods= 0
Subcell Deposition Methods= 0
Advection Scheme= 1
Matrix Solver= 0
Implicit Weighting Factor= 1
Maximum Outer Loop Convergence Iterations= 5
Convergence Maximum Absolute= 0.001
Convergence RMSE= 0.0001
Grain Fractions Max Abs Error= 0.001
Max Subgrid Regions= 1
Max Subgrid Length Scale= 3.402823E+38
Initial Layer Thickness= 3.402823E+38
Min Layer Thickness= 3.402823E+38
Max Layer Thickness= 3.402823E+38
Number of Layers= 5

--- DANIELSCK.f01 (steady flow) ---

Flow Title=Flow
Program Version=6.20
Number of Profiles= 1
Profile Names=P100yr
River Rch & RM=DANIELSCK,Main            ,11248
     722
River Rch & RM=DANIELSCK,Main            ,5836
     824
Boundary for River Rch & Prof#=DANIELSCK,Main            , 1
Up Type= 0
Dn Type= 3
Dn Slope=0.01326
DSS Import GetInterval= 0
DSS Import GetPeak= 0
DSS Import FillOption= 0

--- DANIELSCK.g01 (geometry) ---

Geom Title=Geometry
Program Version=6.20

River Reach=DANIELSCK       ,Main
Reach XY= 30
2346046.41560025662908.9746350632346011.48973202663069.618789696
 2345857.6247601663087.912182124     2345257.952      663470.133
     2345124.149      663667.8842344770.97727828663835.840442955
     2344424.585      664688.193     2344019.938      664841.606
     2344114.187      664968.154      2343877.08       665207.05
     2343901.999      665610.423      2343582.19      665987.605
      2343455.25      666026.813     2343487.863      666386.139
     2343289.625      666532.716     2343116.036      666437.653
     2342975.232      666534.534     2343025.744      666647.671
     2342826.253      666658.258      2342475.24      667074.384
2341757.90891253667499.794328859      2341591.19      667716.813
     2341591.117      667875.616     2341297.719      668036.774
      2341060.95        668018.5      2340361.72      668572.985
     2340022.466      668428.007      2339874.09      668492.252
     2339663.117      668429.448     2339748.219       668608.08

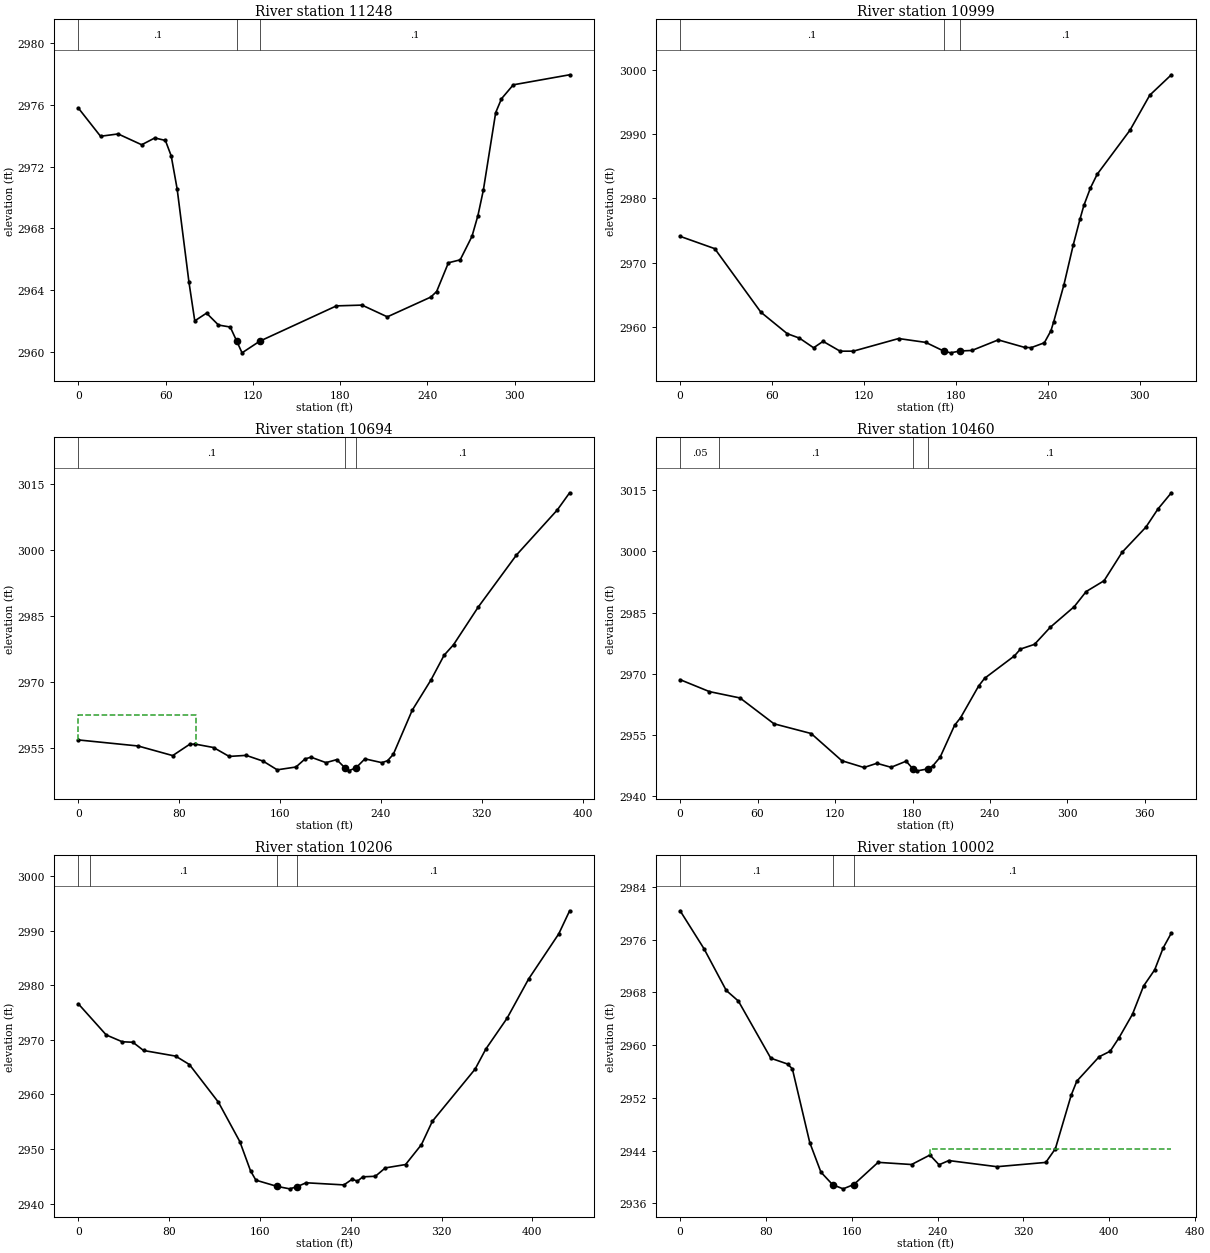
Type RM Length L Ch R = 1 ,11248   ,243,249.5,252
XS GIS Cut Line= 2
2345929.22730786 662895.702724342346262.36862642662951.297008075
#Sta/Elev= 30
       0 2975.79    15.2 2973.97    27.3 2974.12    43.5 2973.42    52.5 2973.86
    59.8  2973.7    63.8  2972.7    67.9 2970.55      76 2964.53      80 2962.02
    88.1 2962.52    96.3 2961.75   104.4 2961.62   108.9  2960.7   112.5 2959.95
   124.6  2960.7   177.4 2962.99     195 2963.04   212.4 2962.28   242.3 2963.56
   246.3 2963.92   254.4 2965.78   262.5 2965.97   270.6 2967.49   274.7 2968.84
   278.4 2970.47   286.9  2975.5   290.9  2976.4     299  2977.3337.7482 2977.95
#Mann= 3 ,-1,0
       0      .1       0   108.9    .045       0   124.6      .1       0
Bank Sta=108.9,124.6
XS Rating Curve= 0 ,0
Exp/Cntr(USF)=0,0
Exp/Cntr=0.3,0.1

Type RM Length L Ch R = 1 ,10999   ,301.7,304.3,300.1
XS GIS Cut Line= 2
2345884.18337011662924.1351765062346002.06777158663222.251729569
#Sta/Elev= 30
       0 2974.08    22.6 2972.16    52.7 2962.25    69.9  2958.9    77.9  2958.2
    87.1  2956.7    93.3  2957.7   104.4 2956.17     113 2956.17   142.6 2958.14
   160.3 2957.54   171.9  2956.2   176.5 2955.91   182.7  2956.2   190.4 2956.28
   207.6 2957.93   224.8 2956.76   229.1 2956.72   237.7 2957.48     242 2959.36
   243.8 2960.76   250.5 2966.55   256.6 2972.78     261  2976.8   263.5 2978.91
   267.8 2981.64   272.2 2983.77   293.6 2990.64   306.5  2996.1320.5779 2999.28
#Mann= 3 ,-1,0
       0      .1       0   171.9    .045       0   182.7      .1       0
Bank Sta=171.9,182.7
XS Rating Curve= 0 ,0
Exp/Cntr(USF)=0,0
Exp/Cntr=0.3,0.1

Type RM Length L Ch R = 1 ,10694   ,233.8,234.4,233.8
XS GIS Cut Line= 2
2345646.72857624663014.5280811162345823.29683592663361.986489187
#Sta/Elev= 30
       0 2956.83    47.3 2955.46    74.8 2953.28    88.2 2955.83    92.7 2955.88
   107.2 2955.11   119.6 2953.09   133.1 2953.33   146.6 2952.01   157.7 2950.05
   172.6 2950.69   179.8 2952.52   184.5 2952.92   196.4 2951.68   204.9 2952.36
   211.3 2950.54   214.3 2949.82   220.2  2950.5   227.3 2952.54   240.8 2951.67
   245.3 2952.13   249.8 2953.56   264.8 2963.56   279.7 2970.44   290.1 2976.04
   297.6 2978.43   317.1 2986.94   347.5 2998.78   379.9    3009   389.7  3012.9
#Mann= 3 ,-1,0
       0      .1       0   211.3    .045       0   220.2      .1       0
#XS Ineff= 2 , 0
           93.66 2962.43
Permanent Ineff=
       F       F
Bank Sta=211.3,220.2
XS Rating Curve= 0 ,0
Exp/Cntr=0.3,0.1

Type RM Length L Ch R = 1 ,10460   ,253.1,253.6,252.1
XS GIS Cut Line= 2
2345472.37294505663177.5361296942345664.17567492 663506.12840335
#Sta/Elev= 30
       0 2968.51    22.7 2965.58    46.4 2964.02    72.7 2957.68   101.5 2955.29
   125.3 2948.61   142.4 2946.95   152.4 2947.98   163.4    2947   175.1  2948.5
   180.2 2946.65   183.8 2946.13  191.77 2946.61   195.5 2947.26   201.4 2949.48
   212.6 2957.31   217.3  2959.2   231.2 2966.94   235.8 2968.83     259 2974.36
   263.6 2976.02   274.5 2977.18   286.7 2981.37   305.3 2986.44   314.5 2990.14
   328.4  2992.8   342.3 2999.76   360.8 3005.96   370.1  3010.4   380.5 3014.39
#Mann= 4 ,-1,0
       0     .05       0      30      .1       0   180.2    .045       0
  191.77      .1       0
Bank Sta=180.2,191.77
XS Rating Curve= 0 ,0
Exp/Cntr(USF)=0,0
Exp/Cntr=0.3,0.1

Type RM Length L Ch R = 1 ,10206   ,204.6,204.4,200.8
XS GIS Cut Line= 2
2345252.52151774663296.4059040032345481.26897982663663.944460462
#Sta/Elev= 30
       0 2976.59    24.5 2970.91    38.6 2969.66      48 2969.57    57.4 2968.06
    85.7 2967.03    97.8 2965.49   123.4 2958.58   142.3 2951.35   151.7 2946.01
   156.4 2944.31   175.2 2943.16   186.2 2942.72  192.69 2943.12   200.7 2943.83
     234 2943.44   241.3 2944.49   245.9 2944.12   250.6 2944.92   261.7 2945.02
   270.4 2946.55   288.3 2947.17   302.3 2950.82   311.9 2955.09   349.6 2964.65
     359 2968.31   377.8 2973.98   396.7 2981.14   423.3 2989.42   432.9 2993.65
#Mann= 4 ,-1,0
       0     .06       0      10      .1       0   175.2    .045       0
  192.69      .1       0
Bank Sta=175.2,192.69
XS Rating Curve= 0 ,0
Exp/Cntr=0.3,0.1

Type RM Length L Ch R = 1 ,10002   ,289.1,293.4,292.6
XS GIS Cut Line= 2
2345089.63727436663423.9988751572345380.96398496663777.088854558
#Sta/Elev= 30
       0 2980.38    22.3 2974.61      43 2968.29    54.3 2966.68    84.5 2958.01
   100.1 2957.13   104.6  2956.4   120.8 2945.22   131.2 2940.73   142.1 2938.82
   151.9 2938.19  161.87 2938.84   184.5 2942.21   215.7 2941.88   232.8 2943.32
   241.3 2941.84   250.4 2942.48   295.3 2941.55   340.8  2942.2   349.7 2944.27
   364.5 2952.42   369.7 2954.53   390.5 2958.23   400.8 2959.07     409  2961.1
   421.6 2964.69   431.9 2968.96   442.3 2971.43   450.2 2974.75   457.8    2977
#Mann= 3 ,-1,0
       0      .1       0   142.1    .045       0  161.87      .1       0
#XS Ineff= 2 , 0
                           232.6         2944.16
Permanent Ineff=
       F       F
Bank Sta=142.1,161.87
XS Rating Curve= 0 ,0
Exp/Cntr(USF)=0,0
Exp/Cntr=0.3,0.1

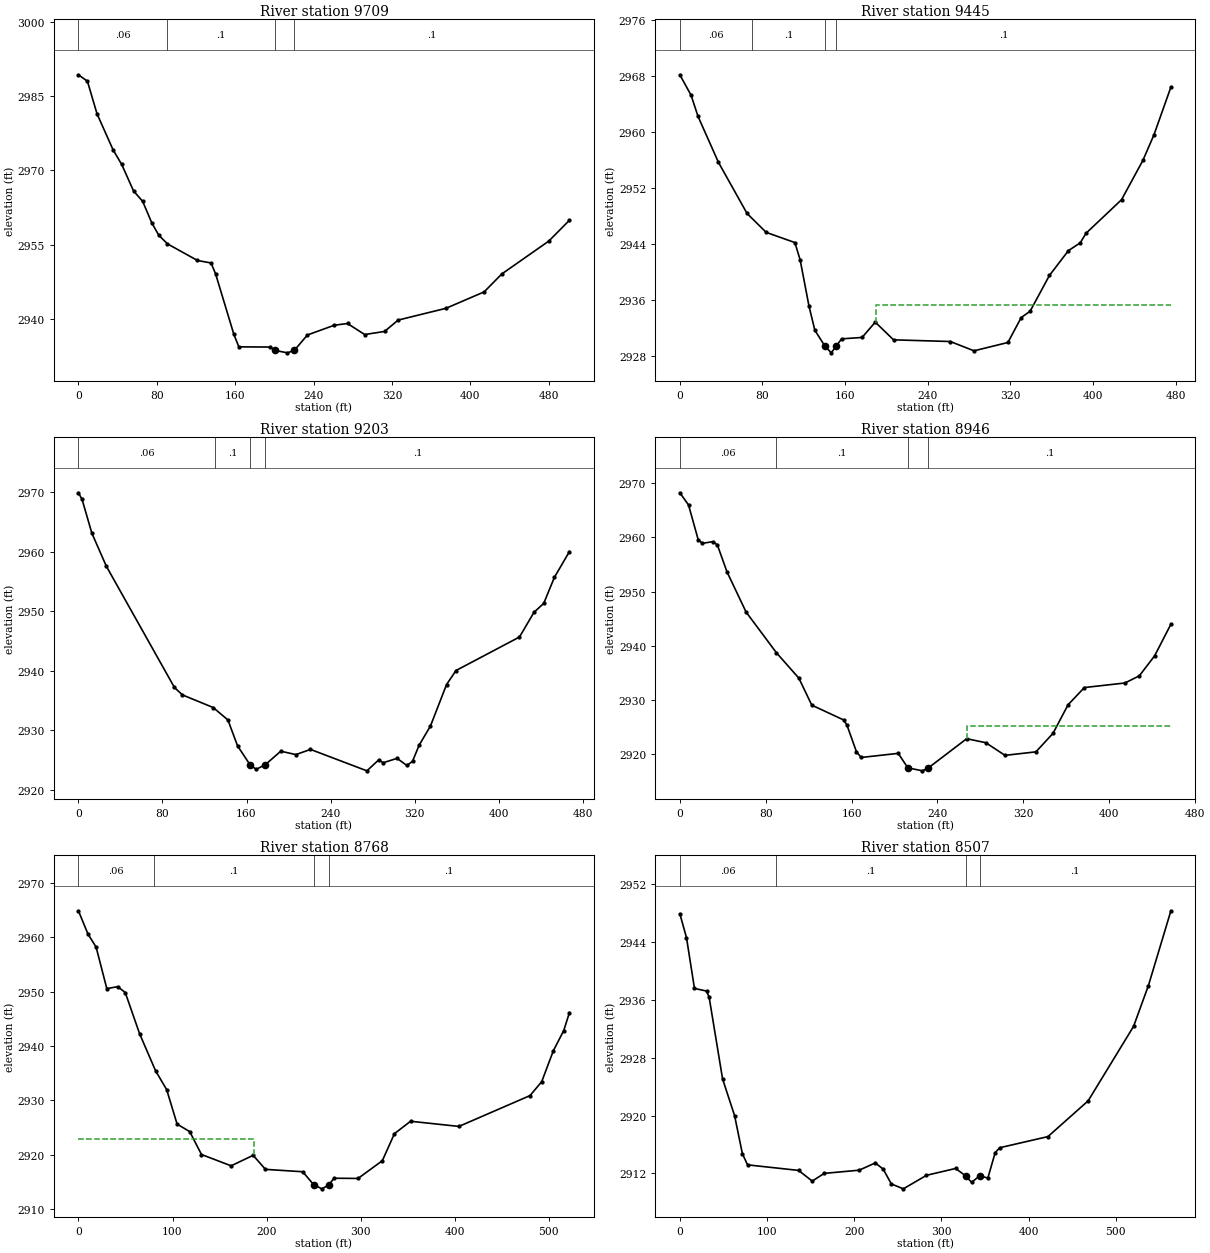
Type RM Length L Ch R = 1 ,9709    ,263.5,263.4,262.2
XS GIS Cut Line= 2
2344887.89200342 663520.866556652345144.76164248663951.302055573
#Sta/Elev= 30
       0 2989.34     9.2 2988.04      19 2981.45    35.4 2974.17    44.2 2971.21
    56.3 2965.86    65.6 2963.75    74.9 2959.41    82.1  2956.9    90.9 2955.17
   121.5 2951.81   135.4  2951.3   140.1 2949.07   158.7 2936.87   163.8 2934.35
     196 2934.31   200.7 2933.63   213.4 2933.14  220.47 2933.65   233.8 2936.75
   261.2 2938.72   274.7 2939.07   292.2 2936.84   312.5 2937.46   326.4 2939.76
   375.2 2942.14   414.2 2945.46   432.2 2949.08   480.2 2955.73   501.3 2959.94
#Mann= 4 ,-1,0
       0     .06       0      90      .1       0   200.7    .045       0
  220.47      .1       0
Bank Sta=200.7,220.47
XS Rating Curve= 0 ,0
Exp/Cntr=0.3,0.1

Type RM Length L Ch R = 1 ,9445    ,243,242.2,239
XS GIS Cut Line= 2
2344693.49917822663708.6163638782344981.68970927664086.751710356
#Sta/Elev= 30
       0 2968.18    10.9 2965.25    17.6 2962.23    37.4 2955.65    65.1 2948.34
    83.6 2945.64   111.4 2944.18   116.5 2941.69     125 2935.12   130.7 2931.64
  140.26 2929.42   146.6 2928.41   151.6 2929.42   156.6 2930.41   176.4 2930.61
   189.2  2932.8   206.9 2930.27   261.8 2930.03   284.8  2928.7   317.6 2929.89
   330.5 2933.46   339.1 2934.36   357.8 2939.48   376.2 2943.03   387.6 2944.14
   393.3 2945.52   427.6 2950.31   448.3 2955.94     459 2959.59   475.4 2966.42
#Mann= 4 ,-1,0
       0     .06       0      70      .1       0  140.26    .045       0
   151.6      .1       0
#XS Ineff= 2 , 0
                          190.24         2935.22
Permanent Ineff=
       F       F
Bank Sta=140.26,151.6
XS Rating Curve= 0 ,0
Exp/Cntr(USF)=0,0
Exp/Cntr=0.3,0.1

Type RM Length L Ch R = 1 ,9203    ,256.2,256.8,256.2
XS GIS Cut Line= 2
2344505.13764152663928.9009811422344909.35608178664163.608650951
#Sta/Elev= 30
       0 2969.87     3.5 2968.75    12.8 2963.08    26.6 2957.52    91.4 2937.15
      99  2935.9   128.3 2933.78   142.3 2931.69   151.5 2927.33   163.4 2924.15
   169.2 2923.39     178 2924.19   192.6 2926.44     207 2925.87   220.9 2926.74
   274.6 2923.14   285.7 2924.96   290.3 2924.51   303.3 2925.24   312.6 2924.04
     318 2924.74   324.3 2927.45   335.1 2930.68   350.4 2937.64   359.4    2940
   419.8 2945.63   433.7  2949.8   442.9 2951.28   453.1 2955.68   467.4    2960
#Mann= 4 ,-1,0
       0     .06       0     130      .1       0   163.4    .045       0
     178      .1       0
Bank Sta=163.4,178
XS Rating Curve= 0 ,0
Exp/Cntr=0.3,0.1

Type RM Length L Ch R = 1 ,8946    ,179.1,178.5,177.5
XS GIS Cut Line= 2
2344368.88769776664147.7854411552344778.53930082664351.227069763
#Sta/Elev= 30
       0 2968.19     8.1 2965.95    17.1 2959.56    21.1 2958.88    30.5 2959.18
    34.9 2958.62    43.9 2953.64    61.7 2946.23      90 2938.72   110.9 2934.04
   122.9 2929.08   152.7 2926.34   155.7 2925.38   164.5  2920.5   168.9 2919.44
   203.4  2920.2   212.4 2917.53     226 2916.98   231.4 2917.51   267.2  2922.9
     285 2922.16   302.9 2919.83   331.7 2920.48   347.6 2923.89   361.6 2929.14
   376.8 2932.32   414.6 2933.16     428 2934.48   442.2 2938.15   457.4 2943.98
#Mann= 4 ,-1,0
       0     .06       0      90      .1       0   212.4    .045       0
   231.4      .1       0
#XS Ineff= 2 , 0
                          267.54         2925.32
Permanent Ineff=
       F       F
Bank Sta=212.4,231.4
XS Rating Curve= 0 ,0
Exp/Cntr(USF)=0,0
Exp/Cntr=0.3,0.1

Type RM Length L Ch R = 1 ,8768    ,259,260.4,261.4
XS GIS Cut Line= 3
2344275.48121098664275.6455428632344422.52488512664379.326468769
2344741.89049171664501.535688616
#Sta/Elev= 30
       0 2964.84    10.2 2960.55    18.8 2958.17    30.2 2950.53    41.8  2950.9
    49.8 2949.81    65.1 2942.21      82 2935.44    93.8 2931.97   104.9 2925.63
   118.3 2924.26   130.8 2920.05   162.3 2917.97   185.7  2919.9   198.8 2917.32
   238.4 2916.88   250.2 2914.47   258.8 2913.74  266.08 2914.45   271.6 2915.69
   297.2 2915.65     323 2918.91   335.9 2923.88     353 2926.16   404.4 2925.21
     480 2930.88   492.4 2933.44   504.8 2939.13   515.8 2942.83   521.9 2946.14
#Mann= 4 ,-1,0
       0     .06       0      80      .1       0   250.2    .045       0
  266.08      .1       0
#XS Ineff= 2 , 0
          186.34 2922.86
Permanent Ineff=
       F       F
Bank Sta=250.2,266.08
XS Rating Curve= 0 ,0
Exp/Cntr=0.3,0.1

Type RM Length L Ch R = 1 ,8507    ,298.9,304.1,305.6
XS GIS Cut Line= 2
2344153.59586091 664485.888857672344642.60195946664765.084907181
#Sta/Elev= 30
       0 2947.93     7.6 2944.64    16.8 2937.59    30.6 2937.23    33.6 2936.38
      49 2925.07    62.8 2919.98    71.7 2914.73    77.6 2913.17   136.2  2912.4
   151.8 2910.92   165.6 2911.99   205.6 2912.43   224.2 2913.44   233.3 2912.56
   242.5 2910.53   256.3 2909.85   282.8 2911.72   316.2 2912.67  327.67 2911.65
   334.6 2910.74   343.8 2911.66   353.2 2911.34   361.6 2914.86   366.8 2915.54
   422.1 2917.08   468.2 2922.03   520.3 2932.34   537.3 2937.98   563.1 2948.34
#Mann= 4 ,-1,0
       0     .06       0     110      .1       0  327.67    .045       0
   343.8      .1       0
Bank Sta=327.67,343.8
XS Rating Curve= 0 ,0
Exp/Cntr(USF)=0,0
Exp/Cntr=0.3,0.1

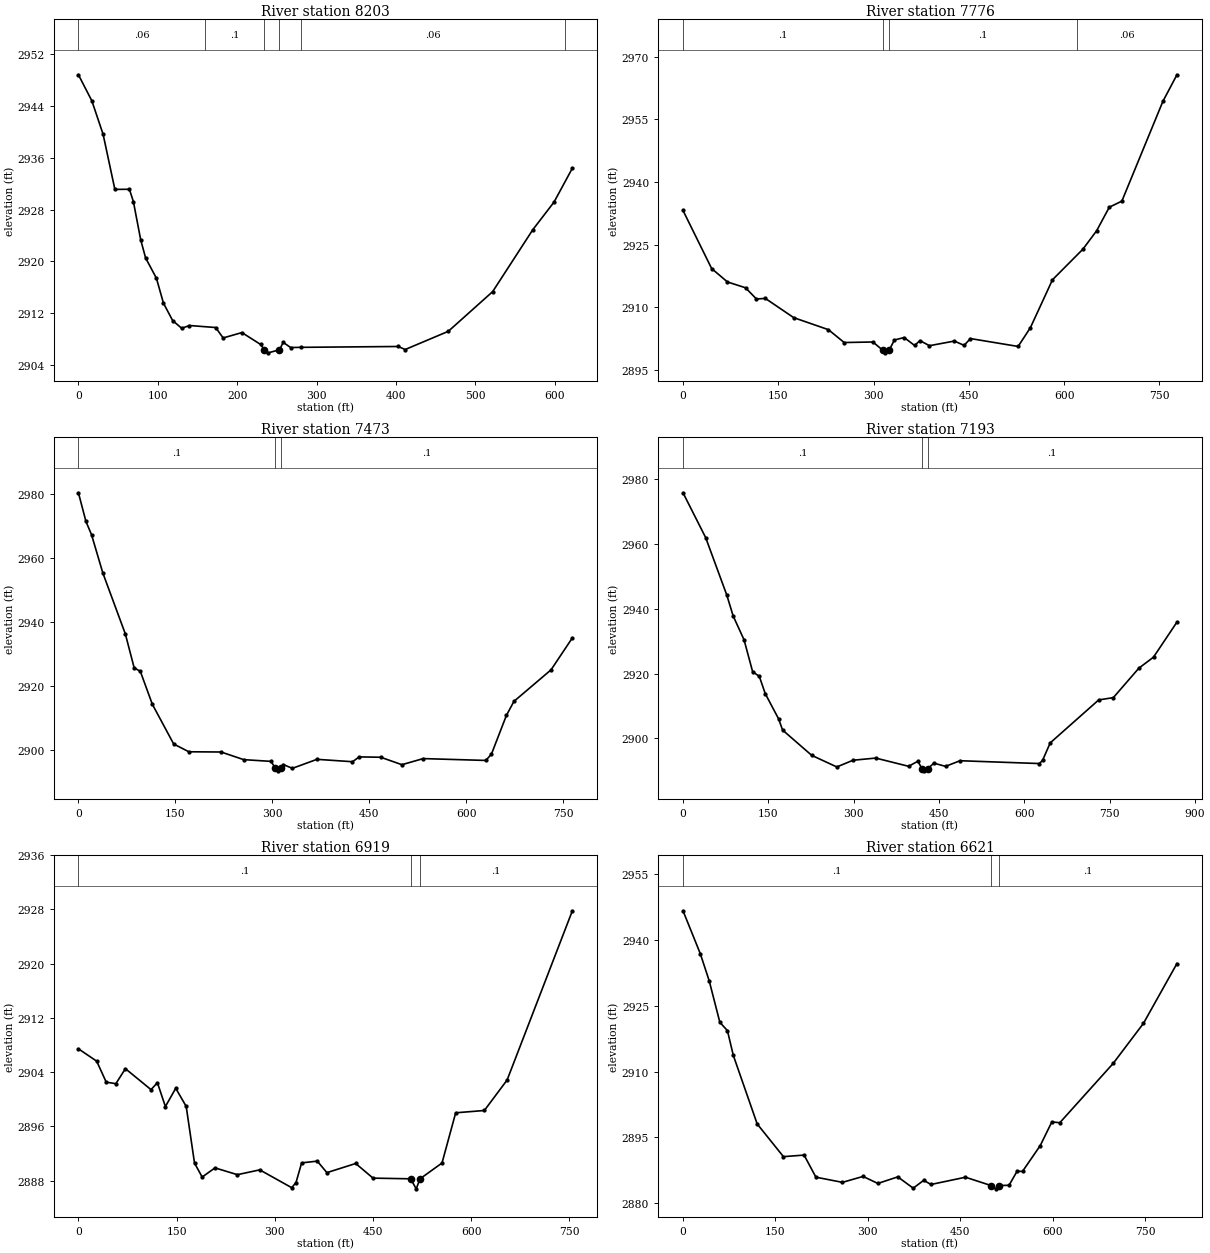
Type RM Length L Ch R = 1 ,8203    ,431.5,427.7,421.4
XS GIS Cut Line= 3
 2344083.1626362664546.8403312152344345.61025807664964.377768609
2344447.53104244665043.292669827
#Sta/Elev= 30
       0 2948.83    16.9 2944.81    31.1 2939.63    45.9 2931.13    64.2 2931.15
    69.2 2929.26    78.4 2923.36    84.6 2920.55    98.2 2917.42   107.1 2913.56
   118.7 2910.87   130.1 2909.68   139.8 2910.11   172.8  2909.8   182.3 2908.19
   205.9 2909.02   229.5 2907.18   234.3 2906.35     239 2905.89   253.2 2906.36
   257.9  2907.5   267.3 2906.71     280 2906.74   402.8 2906.87   411.5  2906.4
   465.8 2909.21   521.7 2915.34   572.3 2924.91     599 2929.17   622.1  2934.4
#Mann= 6 ,-1,0
       0     .06       0     160      .1       0   234.3    .045       0
   253.2      .1       0     280     .06       0  613.17      .1       0
Bank Sta=234.3,253.2
XS Rating Curve= 0 ,0
Exp/Cntr=0.3,0.1

Type RM Length L Ch R = 1 ,7776    ,302.6,303,301.3
XS GIS Cut Line= 2
2343843.82533354664799.963986246 2344469.9513854665260.885275084
#Sta/Elev= 30
       0 2933.18    45.1 2919.26      70 2916.05    98.4 2914.66   115.6 2911.97
   129.6 2912.11   174.3  2907.5   228.9 2904.62   253.7 2901.54   298.9 2901.67
   314.8 2899.65   318.7 2899.07   324.4 2899.66   332.7 2902.14   348.1 2902.74
   364.5 2900.84     373    2902   387.9 2900.78   427.1 2901.89   442.5 2900.86
   452.4 2902.49   527.5  2900.6   546.8 2905.09   581.6 2916.58   629.5 2923.91
   651.1 2928.32     671 2933.96   690.8 2935.42   755.4 2959.33   777.5 2965.69
#Mann= 4 ,-1,0
       0      .1       0   314.8    .045       0   324.4      .1       0
     620     .06       0
Bank Sta=314.8,324.4
XS Rating Curve= 0 ,0
Exp/Cntr(USF)=0,0
Exp/Cntr=0.3,0.1

Type RM Length L Ch R = 1 ,7473    ,277.2,279.4,278.1
XS GIS Cut Line= 2
2343638.97142739665006.4699400262344288.22614607665409.569561806
#Sta/Elev= 30
       0 2980.47    11.6 2971.52    20.3 2967.35    37.7 2955.43    72.6 2936.33
    86.2 2925.76    95.8 2924.62   114.4 2914.32   147.4 2901.92   170.9 2899.49
   220.7 2899.42   255.7 2897.03     298 2896.49   304.9 2894.28   308.5 2893.53
  313.42 2894.28   316.9 2895.51     331 2894.31   369.1 2897.13     424 2896.38
   434.6 2897.89   467.7 2897.78   500.5 2895.45   533.4 2897.36   630.3 2896.78
     639 2898.76   662.2 2910.88   673.8 2915.25   731.2 2925.11   764.2  2935.1
#Mann= 3 ,-1,0
       0      .1       0   304.9    .045       0  313.42      .1       0
Bank Sta=304.9,313.42
XS Rating Curve= 0 ,0
Exp/Cntr(USF)=0,0
Exp/Cntr=0.3,0.1

Type RM Length L Ch R = 1 ,7193    ,273.8,274,276.5
XS GIS Cut Line= 2
2343523.12519815665114.3539151812344202.49598282665654.835321971
#Sta/Elev= 30
       0 2975.78    39.8 2961.96    76.8 2944.29    88.2 2937.74   107.3  2930.4
   122.3 2920.61   134.2 2919.09   144.5 2913.81   167.9 2906.04   175.1 2902.54
   226.2 2894.75   270.3 2891.17   298.8 2893.24   338.7 2893.91   396.5 2891.37
   412.7 2892.93  420.21 2890.59   424.1 2889.97   429.8 2890.58   440.9 2892.34
   461.4 2891.35   486.9 2893.09   626.2 2892.22   631.9 2893.19   645.4  2898.6
   730.6 2911.86   756.3 2912.56   801.2 2921.66   826.9 2925.05   868.1 2935.87
#Mann= 3 ,-1,0
       0      .1       0  420.21    .045       0   429.8      .1       0
Bank Sta=420.21,429.8
XS Rating Curve= 0 ,0
Exp/Cntr=0.3,0.1

Type RM Length L Ch R = 1 ,6919    ,296.3,297.8,292.9
XS GIS Cut Line= 2
2343481.37325878665320.865188397 2344099.2010754665754.428568478
#Sta/Elev= 30
       0 2907.43    27.9 2905.61    42.5 2902.51    57.2 2902.29    71.8  2904.5
   110.9 2901.41   120.7 2902.43   132.9 2898.91   148.7 2901.61   164.7 2898.93
   177.4 2890.57   189.1 2888.51   208.7 2889.86   242.9 2888.86   277.1 2889.57
   325.9 2886.94   332.5  2887.7   341.1  2890.6     365 2890.86   379.7 2889.16
   423.7 2890.51   450.2 2888.35   507.6 2888.25   516.2 2886.77     522 2888.25
   555.6 2890.58   576.5 2897.99   620.3 2898.33   655.1 2902.83   754.8  2927.8
#Mann= 3 ,-1,0
       0      .1       0   507.6    .045       0     522      .1       0
Bank Sta=507.6,522
XS Rating Curve= 0 ,0
Exp/Cntr(USF)=0,0
Exp/Cntr=0.3,0.1

Type RM Length L Ch R = 1 ,6621    ,226.2,226.9,216
XS GIS Cut Line= 2
2343343.95395797665506.6032274052344013.81393835665946.798242147
#Sta/Elev= 30
       0 2946.68      28 2936.92    42.5 2930.71    59.8 2921.23    72.1 2919.34
    81.6 2913.71   120.4 2898.05     163 2890.59   196.5 2890.95   215.7 2885.91
   258.7 2884.73   292.2 2886.08   316.2 2884.48   348.6 2885.98   373.6  2883.4
   390.7  2885.2   402.3 2884.24   458.4  2885.9     500    2884   507.6 2883.25
   512.4    2884   529.1 2884.06   542.1 2887.25     551 2887.24   579.7  2893.1
   598.6 2898.52   611.5 2898.33   698.1 2911.86   747.2 2920.99   801.6 2934.64
#Mann= 3 ,-1,0
       0      .1       0     500    .045       0   512.4      .1       0
Bank Sta=500,512.4
XS Rating Curve= 0 ,0
Exp/Cntr=0.3,0.1

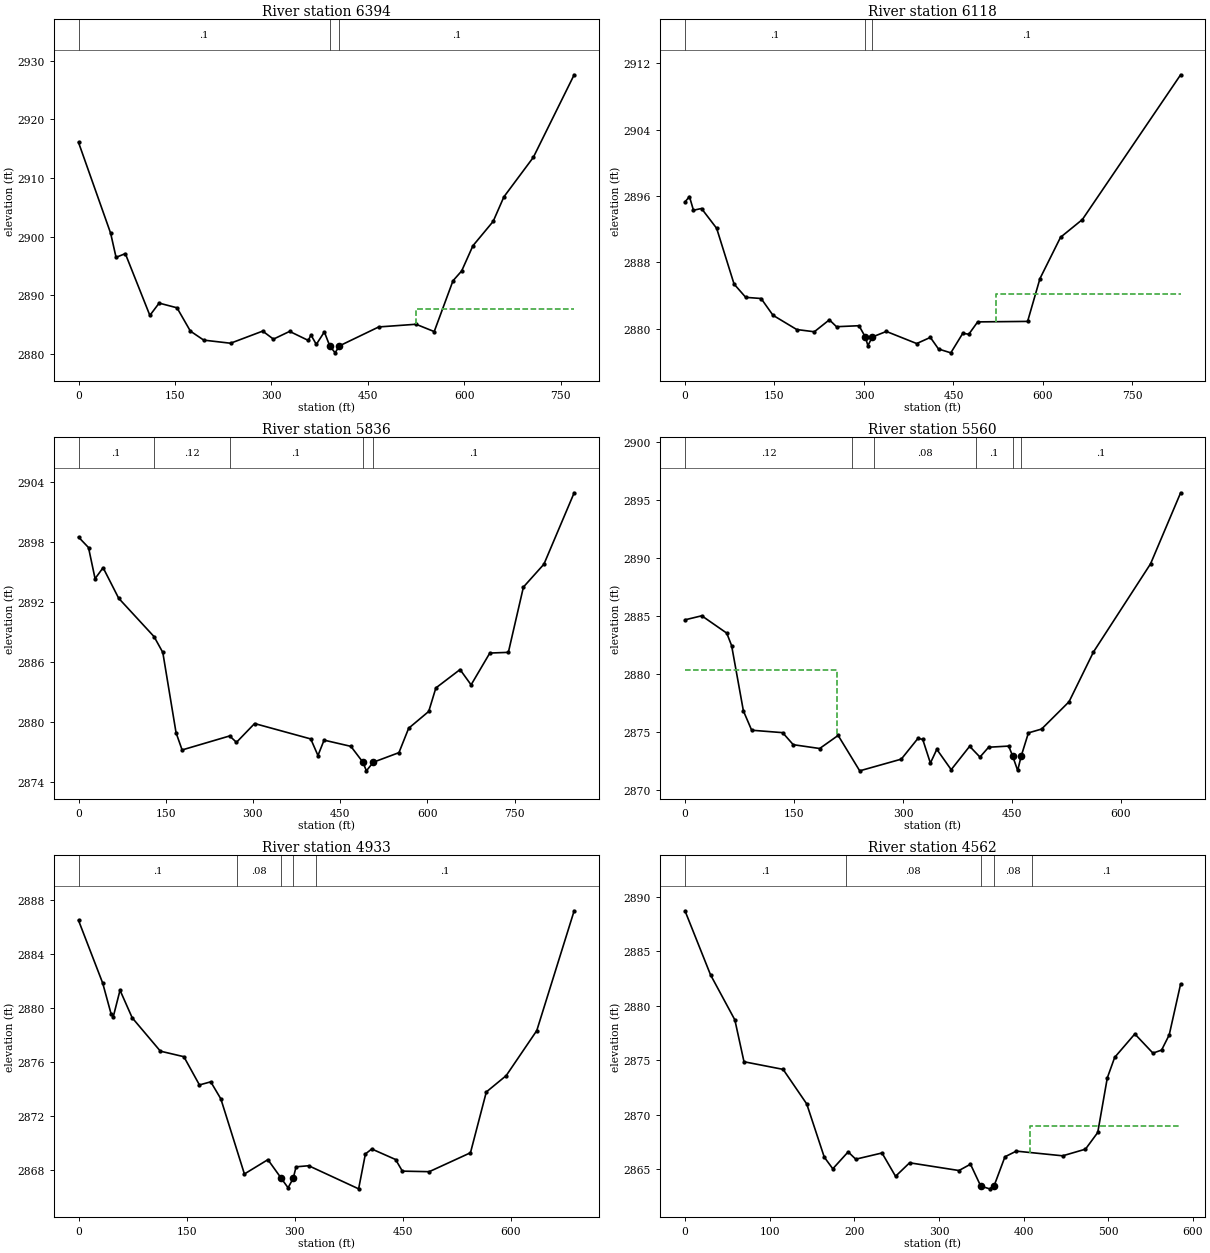
Type RM Length L Ch R = 1 ,6394    ,270.4,276.1,277.6
XS GIS Cut Line= 3
2343304.77446207665652.3091790162343384.11475862665773.398185052
 2343985.0903385665949.477090054
#Sta/Elev= 30
       0 2916.09      50 2900.57    58.4 2896.46    72.8  2897.1     111 2886.55
   125.4 2888.65   153.2 2887.85     174 2883.87   194.8 2882.33   236.5  2881.8
   286.5 2883.87   303.2  2882.5   328.4 2883.82   357.4 2882.28   361.6  2883.2
   369.9  2881.6   382.4 2883.73   390.8 2881.35   399.1 2880.16  405.88 2881.35
     467 2884.58     525 2885.04   553.3 2883.79   582.5 2892.46     596 2894.14
   613.5 2898.44     645  2902.6   661.7 2906.79   707.5 2913.54     771 2927.63
#Mann= 3 ,-1,0
       0      .1       0   390.8    .045       0  405.88      .1       0
#XS Ineff= 2 , 0
                          524.23         2887.57
Permanent Ineff=
       F       F
Bank Sta=390.8,405.88
XS Rating Curve= 0 ,0
Exp/Cntr(USF)=0,0
Exp/Cntr=0.3,0.1

Type RM Length L Ch R = 1 ,6118    ,275,282.4,279.8
XS GIS Cut Line= 3
2343303.72292226665754.4919580852343666.58943223666245.971961812
2343864.37460165666342.120593373
#Sta/Elev= 30
       0 2895.27     7.5 2895.92    14.2 2894.27    27.7 2894.48    53.1 2892.09
    82.3 2885.37   101.8 2883.77   127.6 2883.63   147.5 2881.61   187.3 2879.89
   216.8 2879.62     242 2881.06     254 2880.23   291.7 2880.35   302.3 2878.99
   306.6 2877.95  314.07 2878.99   337.5 2879.66   388.4  2878.2   411.3 2878.94
     425 2877.54   445.6 2877.08   465.7 2879.44   475.7 2879.32   490.6 2880.81
   574.3 2880.87     595 2886.03   629.5 2891.01   666.1 2893.15   830.8  2910.6
#Mann= 3 ,-1,0
       0      .1       0   302.3    .045       0  314.07      .1       0
#XS Ineff= 2 , 0
                          521.44         2884.16
Permanent Ineff=
       F       F
Bank Sta=302.3,314.07
XS Rating Curve= 0 ,0
Exp/Cntr(USF)=0,0
Exp/Cntr=0.3,0.1

Type RM Length L Ch R = 1 ,5836    ,274.8,275.7,271.2
XS GIS Cut Line= 2
2343181.19040143665859.9814935622343725.36038872666516.363810207
#Sta/Elev= 30
       0 2898.51    17.2 2897.46    28.5 2894.35    42.3 2895.45    69.1 2892.39
     130 2888.55     145 2886.97   167.8 2878.94   178.2 2877.22     260 2878.62
   271.7 2877.98   302.9 2879.86   399.5 2878.32   411.9 2876.66   422.4  2878.2
   468.5 2877.58   489.12876.001   495.2 2875.13  507.04 2875.99   551.2 2876.95
   567.9 2879.39   602.4 2881.07   614.7 2883.42   656.3 2885.26   675.3 2883.73
   707.5 2886.91   739.4 2886.98   765.3 2893.51   800.6  2895.8   852.6 2902.94
#Mann= 5 ,-1,0
       0      .1       0     130     .12       0     260      .1       0
   489.1    .045       0  507.04      .1       0
Bank Sta=489.1,507.04
XS Rating Curve= 0 ,0
Exp/Cntr=0.3,0.1

Type RM Length L Ch R = 1 ,5560    ,620.8,627.2,625
XS GIS Cut Line= 2
2343079.99426503666095.2513162762343557.02237396666583.010118868
#Sta/Elev= 30
       0 2884.67    23.1 2885.02    57.5 2883.52    64.2 2882.44    80.4  2876.8
    91.8 2875.13   134.4 2874.92     149 2873.88   185.4 2873.55   210.8 2874.68
   240.5 2871.62   297.7 2872.63   320.6 2874.42   327.2 2874.34   337.8 2872.29
   346.6 2873.48   366.4 2871.72   391.8 2873.74     406 2872.81   417.9 2873.66
   445.6 2873.76   451.2 2872.86   457.9 2871.65   462.6 2872.86   472.7  2874.9
   490.8 2875.23   528.6 2877.59   562.2 2881.89   640.8 2889.51   682.2 2895.65
#Mann= 6 ,-1,0
       0     .12       0     230      .1       0     260     .08       0
     400      .1       0   451.2    .045       0   462.6      .1       0
#XS Ineff= 2 , 0
          208.91  2880.3
Permanent Ineff=
       F       F
Bank Sta=451.2,462.6
XS Rating Curve= 0 ,0
Exp/Cntr(USF)=0,0
Exp/Cntr=0.3,0.1

Type RM Length L Ch R = 1 ,4933    ,362.6,370.6,367.7
XS GIS Cut Line= 2
2342855.45204672666267.7437656342343209.00992702666857.658688351
#Sta/Elev= 30
       0 2886.51    33.6 2881.86    45.3 2879.57    48.3 2879.39    57.6 2881.34
    74.5  2879.3   113.6 2876.83   146.2 2876.42   167.8 2874.33   183.5 2874.56
   197.5  2873.3   230.2 2867.74   262.8  2868.8   281.5 2867.41   281.5  2867.4
   290.8 2866.72   297.9 2867.41   301.9 2868.27   319.4 2868.35   388.7 2866.64
   398.1 2869.22   406.9 2869.59     440 2868.81   449.4 2867.95   486.7 2867.91
   543.9 2869.31   565.9 2873.81   593.5 2875.02   635.9 2878.35   687.8 2887.22
#Mann= 5 ,-1,0
       0      .1       0     220     .08       0   281.5    .045       0
   297.9     .08       0     330      .1       0
Bank Sta=281.5,297.9
XS Rating Curve= 0 ,0
Exp/Cntr(USF)=0,0
Exp/Cntr=0.3,0.1

Type RM Length L Ch R = 1 ,4562    ,224.8,227.3,224.9
XS GIS Cut Line= 2
2342772.84788023666386.4612051532343044.31687493666905.126204671
#Sta/Elev= 30
       0  2888.7    30.2 2882.82    58.9 2878.69    69.7 2874.85   115.9 2874.15
   143.8 2870.98   164.5  2866.1   174.6 2865.03   192.7 2866.58   201.7 2865.91
   232.7 2866.48   248.7 2864.34   265.3 2865.58   323.6 2864.87   337.2 2865.45
   349.32863.445   359.7 2863.19   365.1 2863.47   377.9 2866.13   391.3 2866.65
   446.1 2866.22     473 2866.83   487.5 2868.36   498.8 2873.37   507.5 2875.25
   531.3  2877.4   552.7 2875.64   562.9 2875.92   571.9 2877.31   585.4 2881.99
#Mann= 5 ,-1,0
       0      .1       0     190     .08       0   349.3    .045       0
   365.1     .08       0     410      .1       0
#XS Ineff= 2 , 0
                          407.63         2868.93
Permanent Ineff=
       F       F
Bank Sta=349.3,365.1
XS Rating Curve= 0 ,0
Exp/Cntr(USF)=0,0
Exp/Cntr=0.3,0.1

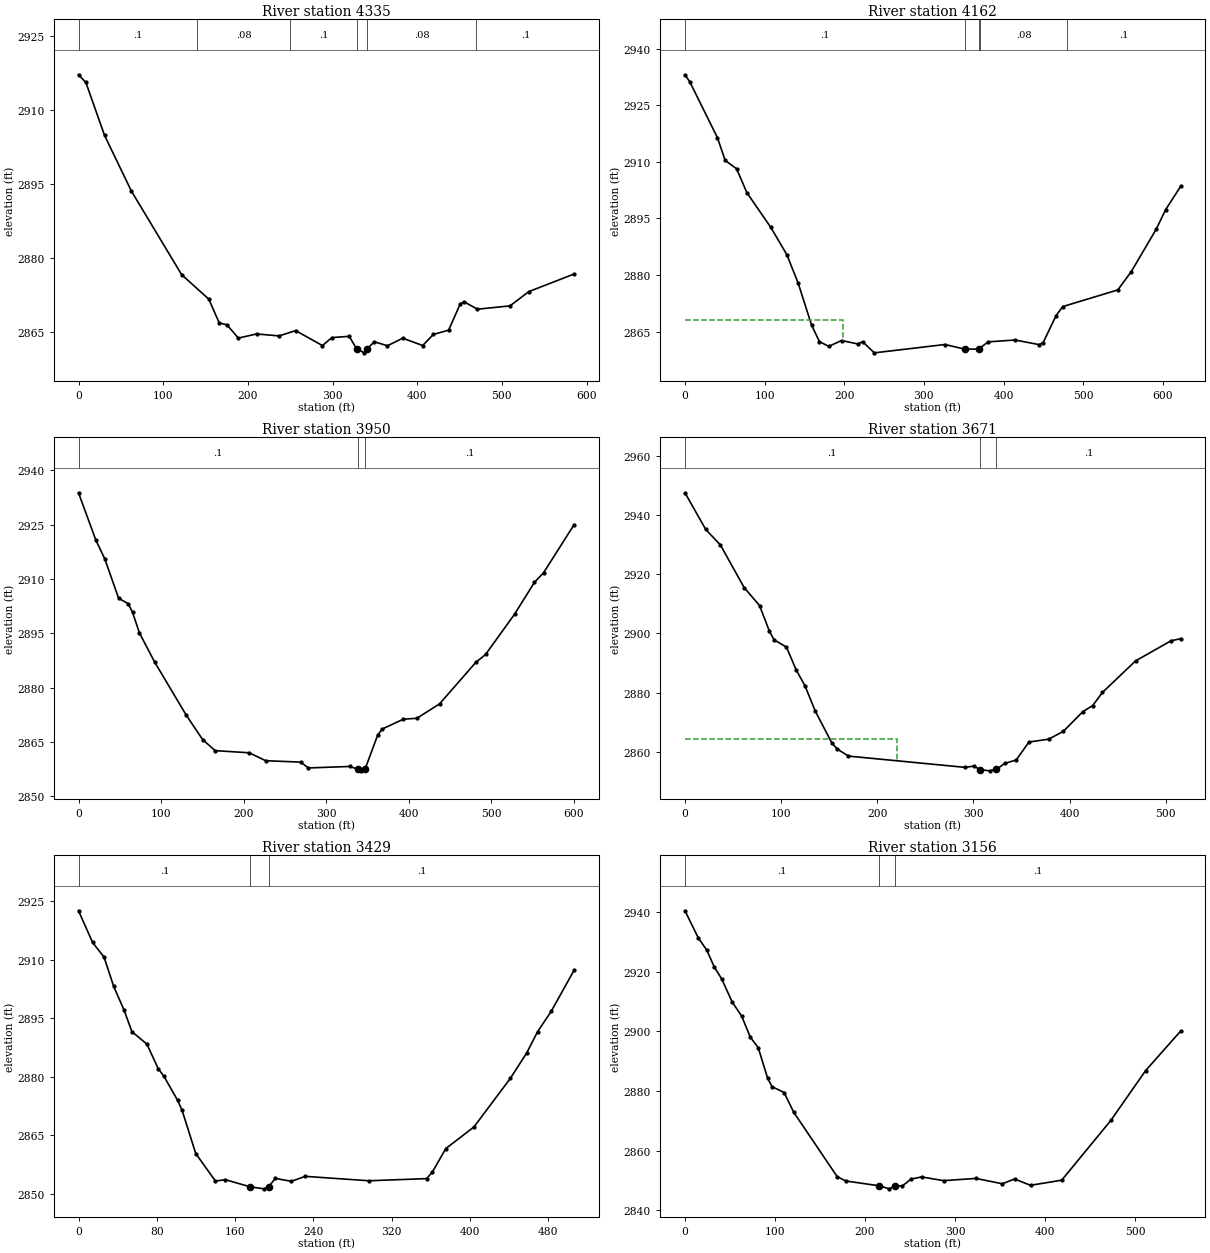
Type RM Length L Ch R = 1 ,4335    ,170.7,172.8,170.6
XS GIS Cut Line= 2
2342615.67684975666429.8988335422342887.14584445 666948.56383306
#Sta/Elev= 30
       0 2917.08     8.7 2915.52    30.8 2904.81    62.4 2893.59   121.8 2876.68
   153.9 2871.73   166.2 2866.93   175.3 2866.54   188.8 2863.86   210.3  2864.7
   236.9  2864.3   256.5 2865.37   288.1 2862.35   299.2 2863.96   319.7 2864.22
  328.43  2861.7   337.5 2860.88   340.7  2861.7   349.5 2863.11   364.9 2862.31
   382.9 2863.84   406.5 2862.36   419.1  2864.6   437.1 2865.46   450.7 2870.71
   455.2 2871.22   471.1  2869.7   509.6 2870.37   531.9 2873.26   585.4 2876.82
#Mann= 6 ,-1,0
       0      .1       0     140     .08       0     250      .1       0
  328.43    .045       0   340.7     .08       0     470      .1       0
Bank Sta=328.43,340.7
XS Rating Curve= 0 ,0
Exp/Cntr(USF)=0,0
Exp/Cntr=0.3,0.1

Type RM Length L Ch R = 1 ,4162    ,213.7,212,210.3
XS GIS Cut Line= 2
2342450.77277239666556.1223861952342814.15507257667061.280359295
#Sta/Elev= 30
       0 2933.08     6.2 2931.15    40.7 2916.43    50.5 2910.37    64.8 2908.18
    77.7 2901.84   107.8 2892.62   127.9  2885.4   142.2 2877.81     159  2866.7
   168.8 2862.37   180.5  2861.1   196.6 2862.66   216.7 2861.76     223 2862.32
   237.8 2859.39   326.5  2861.6   351.1 2860.37   368.6 2860.38   380.7  2862.3
   414.4 2862.79   444.8 2861.56   449.7 2862.12     466 2869.28   474.3 2871.65
   543.4 2876.06   560.3 2880.91   591.5  2892.1   603.6 2897.37   622.3  2903.5
#Mann= 5 ,-1,0
       0      .1       0   351.1    .045       0   368.6      .1       0
     370     .08       0     480      .1       0
#XS Ineff= 2 , 0
          197.82 2868.18
Permanent Ineff=
       F       F
Bank Sta=351.1,368.6
XS Rating Curve= 0 ,0
Exp/Cntr=0.3,0.1

Type RM Length L Ch R = 1 ,3950    ,278.3,279.4,277.4
XS GIS Cut Line= 2
2342318.94324385666741.8926745832342729.62411221667180.273425554
#Sta/Elev= 30
       0 2933.81    20.9 2920.79    31.9 2915.52    48.6 2904.66    60.3 2903.15
    65.5 2900.75    73.9 2895.04    92.2 2887.06   130.5 2872.38   150.4 2865.62
   165.6 2862.55     207 2861.96   226.8 2859.77   269.2 2859.38   278.6 2857.77
   328.6 2858.18   338.8 2857.42   342.8 2856.97  347.25 2857.41   362.6 2866.87
   368.3 2868.55   393.7 2871.24   410.1  2871.5   437.5 2875.46   481.5 2886.94
   493.3 2889.12   528.4 2900.24   552.6 2909.07   563.6  2911.7   600.7 2925.03
#Mann= 3 ,-1,0
       0      .1       0   338.8    .045       0  347.25      .1       0
Bank Sta=338.8,347.25
XS Rating Curve= 0 ,0
Exp/Cntr(USF)=0,0
Exp/Cntr=0.3,0.1

Type RM Length L Ch R = 1 ,3671    ,241,242.4,243.1
XS GIS Cut Line= 2
2342154.83639842666892.2111779052342474.10842036667297.017187363
#Sta/Elev= 30
       0 2947.54    21.6 2935.14    36.9 2929.89    61.5 2915.53    77.6 2909.42
    87.8 2900.79    92.6 2897.86   105.5 2895.41   115.6 2887.74   124.9 2882.27
   135.5 2873.79   152.6 2863.11   158.3 2860.96   170.1 2858.56   291.6 2854.75
   300.7  2855.2   306.4 2854.02   317.1 2853.58     324 2854.04   332.4 2856.07
   344.5 2857.24   357.8 2863.31   378.2 2864.28   393.5 2866.89   413.9 2873.59
   424.1 2875.64   434.3 2880.08   468.7 2890.72   505.6 2897.53   515.6 2898.23
#Mann= 3 ,-1,0
       0      .1       0   306.4    .045       0     324      .1       0
#XS Ineff= 2 , 0
          220.76 2864.49
Permanent Ineff=
       F       F
Bank Sta=306.4,324
XS Rating Curve= 0 ,0
Exp/Cntr=0.3,0.1

Type RM Length L Ch R = 1 ,3429    ,273.5,272.8,272.2
XS GIS Cut Line= 2
2342039.22184773667082.3232745432342298.82461234667517.224813204
#Sta/Elev= 30
       0 2922.56    14.4 2914.44    26.1 2910.69    35.9 2903.22    46.5 2897.13
    54.6 2891.59    69.9 2888.39    81.5 2882.09    87.4 2880.12   101.2 2874.02
   105.8 2871.46   119.8 2860.37   139.9 2853.32   150.1 2853.66   175.7 2851.82
   189.7 2851.32  194.16 2851.83   201.1 2853.99   217.6 2853.25   231.6 2854.52
   296.8 2853.39   355.8 2853.94   361.6 2855.63   375.3 2861.63     404 2867.15
   441.2 2879.59   457.9  2886.1   469.2 2891.61   483.1 2896.82   506.5 2907.36
#Mann= 3 ,-1,0
       0      .1       0   175.7    .045       0  194.16      .1       0
Bank Sta=175.7,194.16
XS Rating Curve= 0 ,0
Exp/Cntr(USF)=0,0
Exp/Cntr=0.3,0.1

Type RM Length L Ch R = 1 ,3156    ,246.5,244.4,242.9
XS GIS Cut Line= 2
2341811.58695355667232.9714298472342119.31204881667689.490287662
#Sta/Elev= 30
       0 2940.34    14.7 2931.31    24.4 2927.05    32.3 2921.66    40.9 2917.44
    52.4  2909.8      63 2905.04    72.6 2897.97    81.3 2894.53    91.9 2884.18
    96.7 2881.42   110.1 2879.47   120.8 2872.84   169.1 2851.26   178.7 2849.83
   215.7 2848.22     227  2847.2  233.21 2848.22   241.4 2848.16   251.1 2850.47
   262.8 2851.19   287.3 2849.94   323.1 2850.69   352.4  2848.9     366 2850.49
   383.8 2848.39   418.4 2850.09     473 2870.12   511.6  2886.8   550.5 2900.05
#Mann= 3 ,-1,0
       0      .1       0   215.7    .045       0  233.21      .1       0
Bank Sta=215.7,233.21
XS Rating Curve= 0 ,0
Exp/Cntr=0.3,0.1