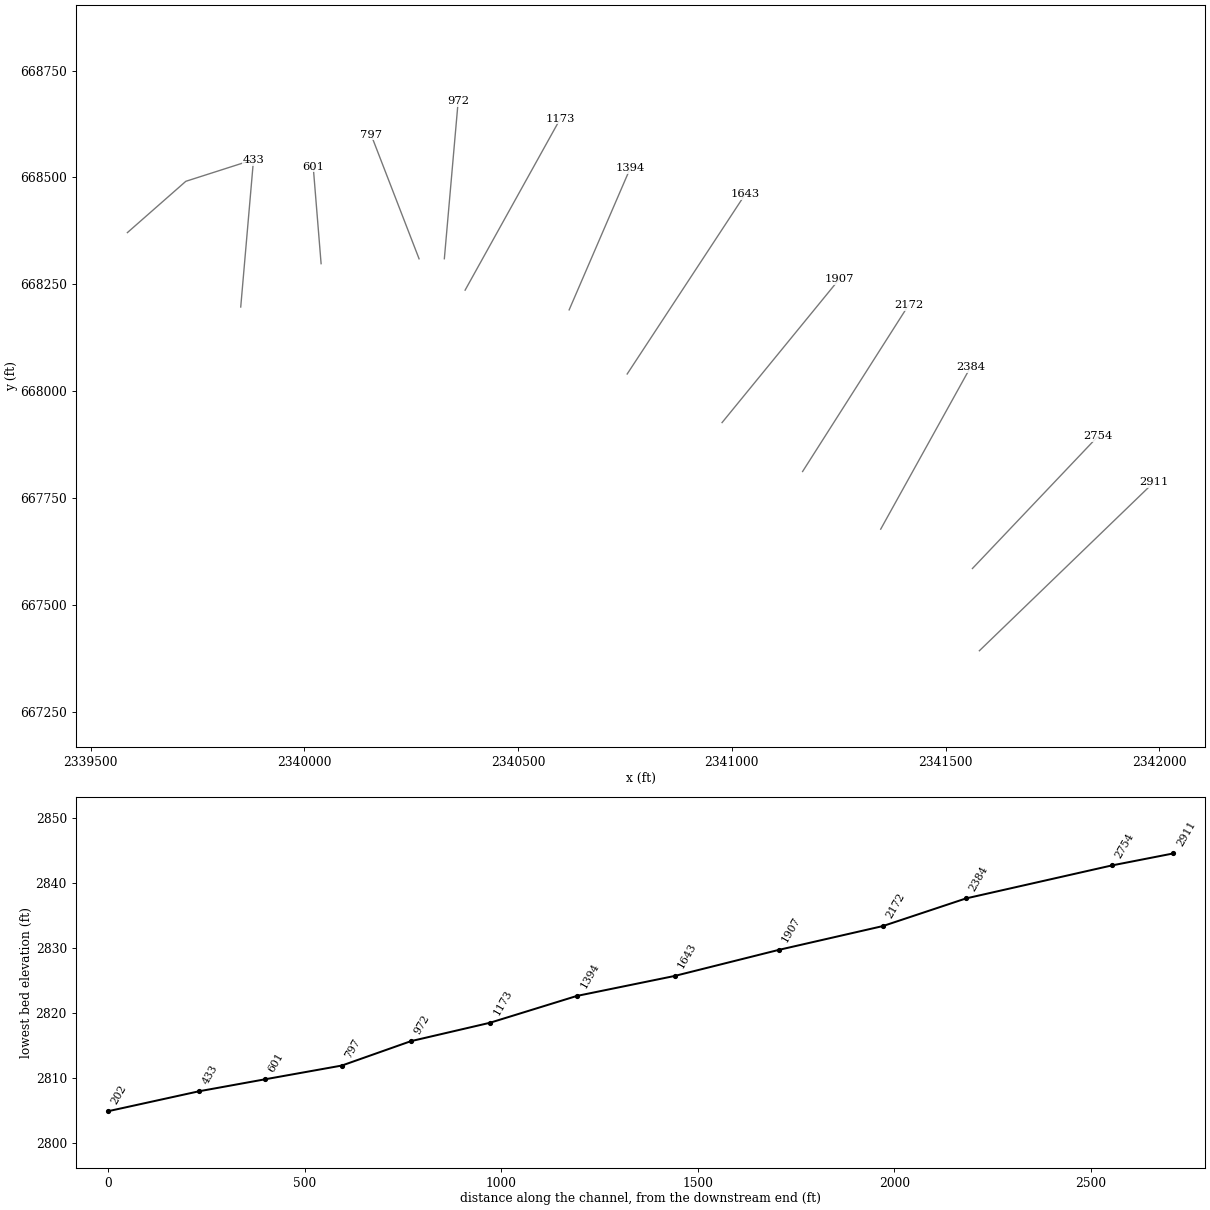
HEC-RAS study DANIELSCK.prj: DANIELSCK

--- DANIELSCK.g01 (geometry) --- (continued)

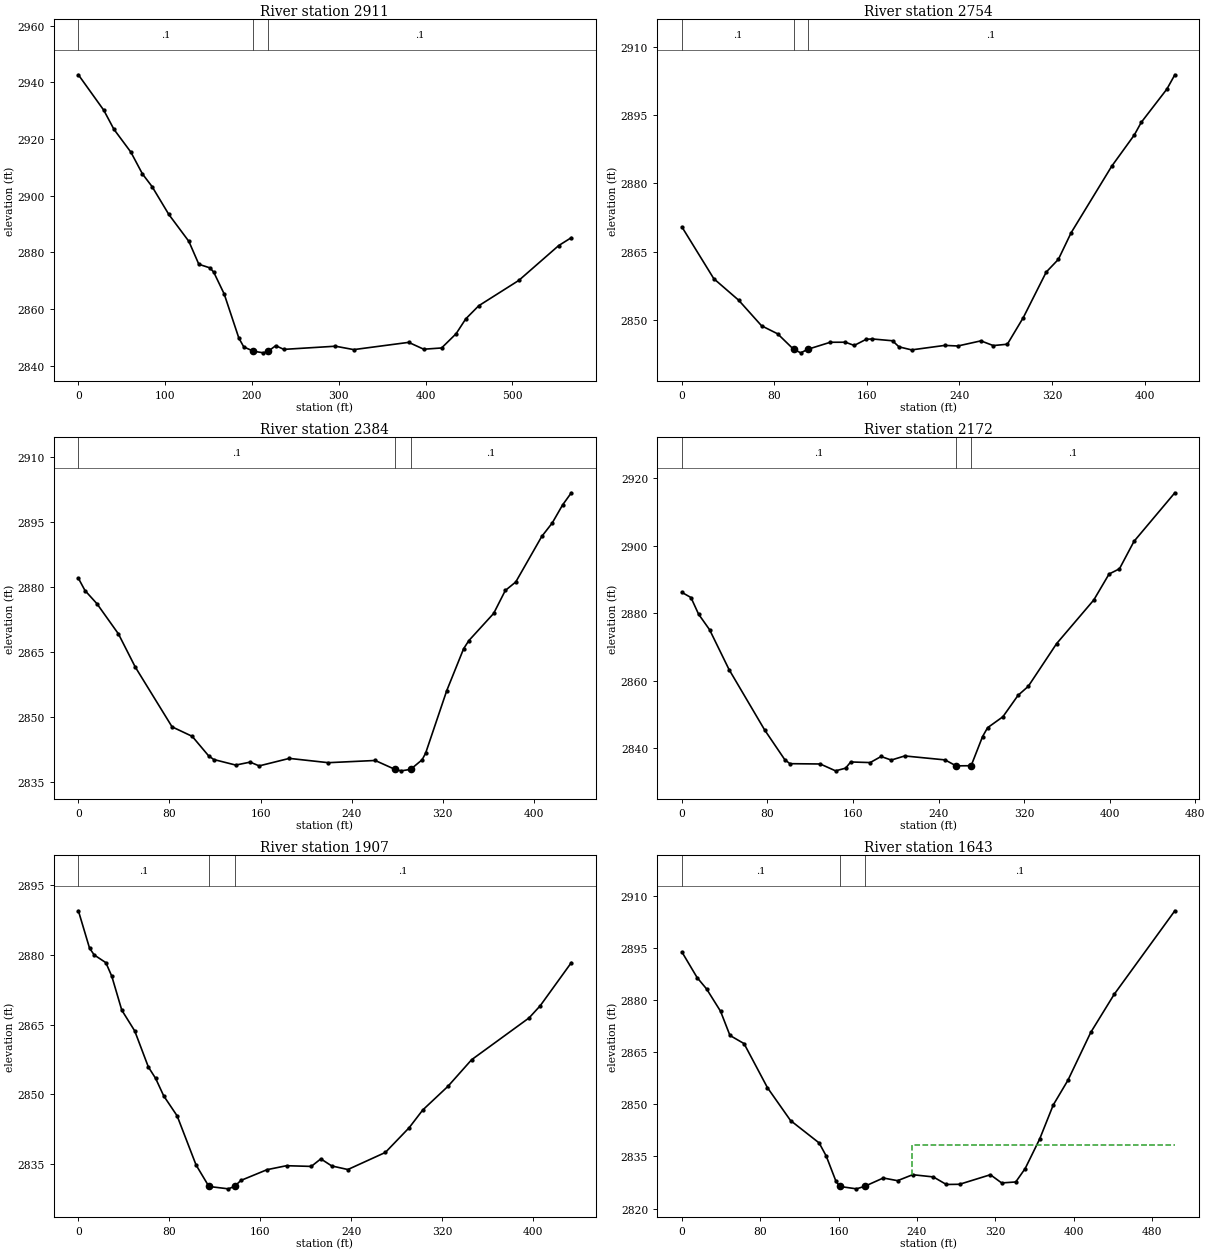
Type RM Length L Ch R = 1 ,2911    ,157.1,157.4,157.1
XS GIS Cut Line= 2
2341579.07065987667392.790389536 2341987.7041456 667787.33306541
#Sta/Elev= 30
       0 2942.72    29.3 2930.19    40.9  2923.5    60.5  2915.4    73.8 2907.72
    84.9 2903.25   104.2 2893.41   127.3  2883.9   138.8 2875.81   151.7 2874.53
     156 2872.99     168 2865.33   184.9 2849.75   190.6 2846.62   201.7 2845.12
   213.2 2844.54   218.9 2845.14   227.4 2847.07   236.7 2845.76   296.2 2846.88
   317.3 2845.68   380.6 2848.24   397.9 2845.82   418.5 2846.26   435.2 2851.28
   446.3 2856.52   461.3 2861.16   507.5 2870.12   553.4 2882.41     568 2885.21
#Mann= 3 ,-1,0
       0      .1       0   201.7    .045       0   218.9      .1       0
Bank Sta=201.7,218.9
XS Rating Curve= 0 ,0
Exp/Cntr(USF)=0,0
Exp/Cntr=0.3,0.1

Type RM Length L Ch R = 1 ,2754    ,367,370.4,368.6
XS GIS Cut Line= 2
2341562.81970408667585.1453294782341856.25541247667894.183932179
#Sta/Elev= 30
       0 2870.44    27.6 2859.02    49.1 2854.28    68.9 2848.64    82.8 2846.87
    96.62843.453   102.8 2842.68  108.81 2843.46   128.3 2845.01   141.4 2845.02
     149 2844.31   159.4 2845.67   164.6 2845.74   182.1 2845.34   187.7    2844
   198.6 2843.33   227.3 2844.32   238.6 2844.19   258.5 2845.32   269.2 2844.28
   281.4 2844.58   295.2 2850.46     315 2860.48   325.5 2863.28   336.5 2869.13
   371.6  2883.8   391.2 2890.71   397.2 2893.49   419.3  2900.8   426.2 2903.96
#Mann= 3 ,-1,0
       0      .1       0    96.6    .045       0  108.81      .1       0
Bank Sta=96.6,108.81
XS Rating Curve= 0 ,0
Exp/Cntr=0.3,0.1

Type RM Length L Ch R = 1 ,2384    ,211.3,211.2,210.4
XS GIS Cut Line= 2
2341348.27097538667677.191490636 2341558.2615258668055.920715456
#Sta/Elev= 30
       0 2882.01     5.8 2879.18    16.3 2876.14    35.2 2869.17    49.9 2861.57
    82.3 2847.75     100 2845.56   114.3  2841.1   118.9 2840.22   138.2 2838.94
   150.9 2839.62   158.8 2838.75   185.3 2840.48   219.5 2839.49   260.7    2840
   278.22837.934   283.6 2837.61   291.82837.948   301.9 2840.15     305 2841.68
   323.6 2856.13   338.4 2865.77     343 2867.64   364.8 2873.91     375 2879.19
   384.2 2881.15     407 2891.64   416.2 2894.74   425.3  2898.9     433 2901.71
#Mann= 3 ,-1,0
       0      .1       0   278.2    .045       0   291.8      .1       0
Bank Sta=278.2,291.8
XS Rating Curve= 0 ,0
Exp/Cntr(USF)=0,0
Exp/Cntr=0.3,0.1

Type RM Length L Ch R = 1 ,2172    ,267,265.1,257.9
XS GIS Cut Line= 2
2341165.55539174667812.0110817772341413.21098201668200.877381354
#Sta/Elev= 30
       0 2886.22     8.5 2884.69    15.6 2879.77    25.9 2875.16    44.1 2863.37
    77.3 2845.52    96.2 2836.68     101 2835.48   129.4 2835.39   143.7 2833.36
   153.1 2834.15   157.9 2835.99   176.1 2835.81   186.3 2837.61   195.8 2836.55
   208.4 2837.77   246.1  2836.6   256.4 2834.84   270.52834.875   281.2 2843.52
   285.9 2846.14   300.2 2849.38   314.4 2855.73   323.9 2858.38   350.4 2871.03
   385.2 2883.97   399.5 2891.66   409.2  2893.2   422.8 2901.33     461 2915.72
#Mann= 3 ,-1,0
       0      .1       0   256.4    .045       0   270.5      .1       0
Bank Sta=256.4,270.5
XS Rating Curve= 0 ,0
Exp/Cntr=0.3,0.1

Type RM Length L Ch R = 1 ,1907    ,263,264.7,265.6
XS GIS Cut Line= 2
2340977.16525996667926.4486004772341251.75540068 668262.46022004
#Sta/Elev= 30
       0 2889.44     9.8 2881.43    13.9 2879.95    24.2 2878.29    29.4 2875.38
    38.2 2868.09    49.6 2863.62    61.6 2855.87      68 2853.42    75.1 2849.67
    86.9 2845.38   103.6 2834.81   114.9  2830.2     132 2829.69   137.5 2830.22
     143 2831.49   166.1 2833.81   183.2 2834.66     205 2834.51   213.4 2836.13
     223 2834.61   237.2 2833.84   270.2 2837.51   291.2 2842.84   303.1 2846.63
   325.3 2851.72   346.1 2857.43   396.7 2866.42   406.5 2869.03   433.9  2878.3
#Mann= 3 ,-1,0
       0      .1       0   114.9    .045       0   137.5      .1       0
Bank Sta=114.9,137.5
XS Rating Curve= 0 ,0
Exp/Cntr(USF)=0,0
Exp/Cntr=0.3,0.1

Type RM Length L Ch R = 1 ,1643    ,248.2,248.4,247.3
XS GIS Cut Line= 2
2340755.25086109668040.1398743732341031.60467581668461.019337497
#Sta/Elev= 30
       0 2893.88    15.6 2886.48    25.2 2883.24    39.5  2876.8    49.1 2869.84
    63.5 2867.49    87.4  2854.8     111 2845.34   140.2 2838.89   147.4 2835.14
   157.4 2827.84  161.35 2826.36   178.3 2825.68   186.6 2826.39   205.7  2828.8
   220.3 2828.03   235.7 2829.75   256.8 2829.11   270.1 2826.94   283.6 2826.99
   315.1 2829.74   326.6 2827.38     341 2827.66   350.6 2831.51   365.4    2840
   379.3 2849.82   394.3 2856.94   417.6 2870.71   441.5 2881.66   503.5 2905.73
#Mann= 3 ,-1,0
       0      .1       0  161.35    .045       0   186.6      .1       0
#XS Ineff= 2 , 0
                          235.35          2838.2
Permanent Ineff=
       F       F
Bank Sta=161.35,186.6
XS Rating Curve= 0 ,0
Exp/Cntr=0.3,0.1

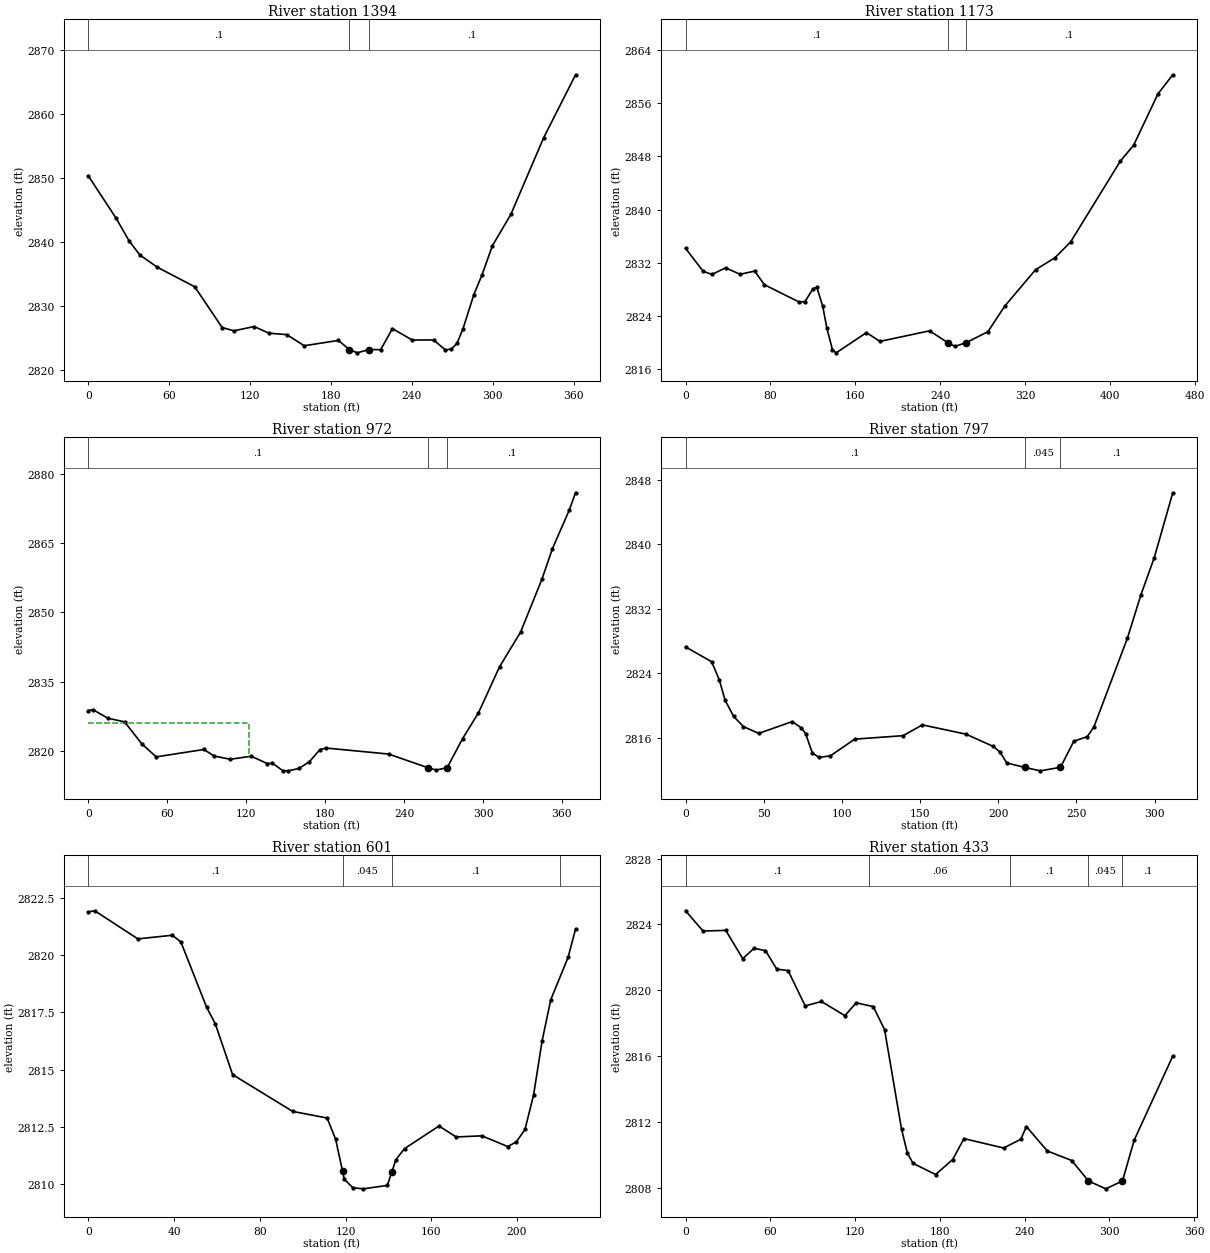
Type RM Length L Ch R = 1 ,1394    ,221.4,221.1,219.8
XS GIS Cut Line= 2
 2340619.4966183668190.1265926832340762.58686423668521.851451238
#Sta/Elev= 30
       0 2850.28    20.7 2843.62    30.2 2840.13    38.2 2837.91    51.2 2835.99
    78.9 2832.94    99.2 2826.57   107.9 2826.05   122.9 2826.72     134 2825.68
   147.1 2825.46   160.1 2823.72   185.4 2824.55   193.6 2823.12   199.4 2822.61
   208.1 2823.12   216.8 2823.11   225.5  2826.4   240.2 2824.61     256 2824.63
   264.7 2823.07   269.1  2823.2   273.4  2824.1   277.8 2826.36   285.9 2831.73
     292 2834.84   299.6 2839.35   313.3 2844.25   337.6 2856.23   361.3 2866.09
#Mann= 3 ,-1,0
       0      .1       0   193.6    .045       0   208.1      .1       0
Bank Sta=193.6,208.1
XS Rating Curve= 0 ,0
Exp/Cntr(USF)=0,0
Exp/Cntr=0.3,0.1

Type RM Length L Ch R = 1 ,1173    ,196.9,201,202.4
XS GIS Cut Line= 2
2340376.14303961 668236.223452392340598.90049455668637.392562974
#Sta/Elev= 30
       0 2834.19    16.5 2830.76    24.8 2830.26    37.7 2831.26    51.4 2830.29
    65.1 2830.77    74.3 2828.72   107.2  2826.1   112.5 2826.19   120.1 2828.13
   123.7 2828.31   129.2 2825.49   133.1  2822.2   138.4 2818.93   141.9 2818.48
   170.4 2821.52   183.1  2820.2   229.9 2821.79   247.3 2819.98   253.7 2819.45
     2642819.985   284.8 2821.66   300.7 2825.51   329.7 2830.98   347.9 2832.77
   362.6 2835.13   409.6 2847.32     422 2849.68     445 2857.42   458.9 2860.28
#Mann= 3 ,-1,0
       0      .1       0   247.3    .045       0     264      .1       0
Bank Sta=247.3,264
XS Rating Curve= 0 ,0
Exp/Cntr=0.3,0.1

Type RM Length L Ch R = 1 ,972     ,171.8,175.5,178.7
XS GIS Cut Line= 2
2340327.57669614668309.729153658 2340359.9736358 668678.73819817
#Sta/Elev= 30
       0 2828.73     3.5 2828.92    14.8 2827.07    27.6 2826.27    40.6 2821.51
    51.6 2818.68    87.8 2820.28    95.8 2818.85   107.9 2818.16   123.9 2818.82
     136 2817.23     140  2817.3     148 2815.66     152 2815.65   160.1 2816.17
   168.1 2817.64   176.1 2820.27   180.9 2820.59   228.3 2819.29   258.4  2816.3
   264.5 2815.82   272.82816.339   284.5 2822.63   296.6 2828.24   312.6 2838.21
   328.6 2845.74   344.8 2857.19   352.8 2863.83   365.5 2872.13   370.4 2875.96
#Mann= 3 ,-1,0
       0      .1       0   258.4    .045       0   272.8      .1       0
#XS Ineff= 2 , 0
          122.24 2825.92
Permanent Ineff=
       F       F
Bank Sta=258.4,272.8
XS Rating Curve= 0 ,0
Exp/Cntr(USF)=0,0
Exp/Cntr=0.3,0.1

Type RM Length L Ch R = 1 ,797     ,197.8,195.7,191.7
XS GIS Cut Line= 2
2340268.44800482668309.5610006512340156.06837671668600.167695235
#Sta/Elev= 30
       0 2827.27    16.7 2825.43    21.6 2823.18    25.3 2820.65    30.8 2818.64
      37 2817.39    46.8 2816.54    68.2 2818.01    74.1 2817.22    76.8 2816.51
    81.1 2814.11    85.4 2813.56    92.7 2813.77   108.2 2815.83   139.1 2816.26
   151.5  2817.6   179.3 2816.45   196.9 2814.92   201.2 2814.22   205.4 2812.88
  217.06 2812.32   226.9  2811.9   239.8 2812.34   248.3 2815.57   256.9 2816.14
   261.2 2817.36   282.6 2828.35   291.2 2833.71   299.8 2838.35   311.6 2846.38
#Mann= 3 ,-1,0
       0      .1       0  217.06    .045       0   239.8      .1       0
Bank Sta=217.06,239.8
XS Rating Curve= 0 ,0
Exp/Cntr(USF)=0,0
Exp/Cntr=0.3,0.1

Type RM Length L Ch R = 1 ,601     ,170.2,167.7,166.8
XS GIS Cut Line= 2
2340039.29891937668298.1474446712340020.86163663668524.662632594
#Sta/Elev= 30
       0  2821.9       3 2821.95    23.1 2820.72    39.2 2820.88    43.2 2820.58
    55.2 2817.72    59.2 2817.01    67.3 2814.78    95.3 2813.17   111.4 2812.88
   115.4 2811.94   118.62810.548   119.4  2810.2   123.4 2809.83   128.2 2809.78
   139.5 2809.93   141.62810.523   143.5 2811.06   147.5 2811.54   163.6 2812.53
   171.6 2812.05   183.6  2812.1   195.7 2811.63   199.7 2811.84   203.7 2812.38
   207.7 2813.88   211.7 2816.26   215.7 2818.05   223.8 2819.91   227.3 2821.15
#Mann= 4 ,-1,0
       0      .1       0   118.6    .045       0   141.6      .1       0
     220     .06       0
Bank Sta=118.6,141.6
XS Rating Curve= 0 ,0
Exp/Cntr(USF)=0,0
Exp/Cntr=0.3,0.1

Type RM Length L Ch R = 1 ,433     ,235.3,231.3,221.2
XS GIS Cut Line= 2
2339851.29266511668196.8152022942339881.12814292668540.383265085
#Sta/Elev= 30
       0 2824.83    12.4  2823.6    28.5 2823.64    40.5 2821.92    48.5 2822.55
    56.6 2822.41    64.6 2821.28    72.6  2821.2    84.7 2819.05    96.2 2819.32
   112.8 2818.46   120.8 2819.24   132.9 2819.01   140.9 2817.61   152.9 2811.57
     157 2810.12     161 2809.49     177 2808.81   189.1 2809.72   197.1 2810.99
   225.2 2810.42   237.3 2810.95   241.3 2811.72   256.1 2810.24   273.4 2809.66
   285.2 2808.42   297.5 2807.94   309.32808.419   317.6  2810.9   344.9    2816
#Mann= 5 ,-1,0
       0      .1       0     130     .06       0     230      .1       0
   285.2    .045       0   309.3      .1       0
Bank Sta=285.2,309.3
XS Rating Curve= 0 ,0
Exp/Cntr(USF)=0,0
Exp/Cntr=0.3,0.1

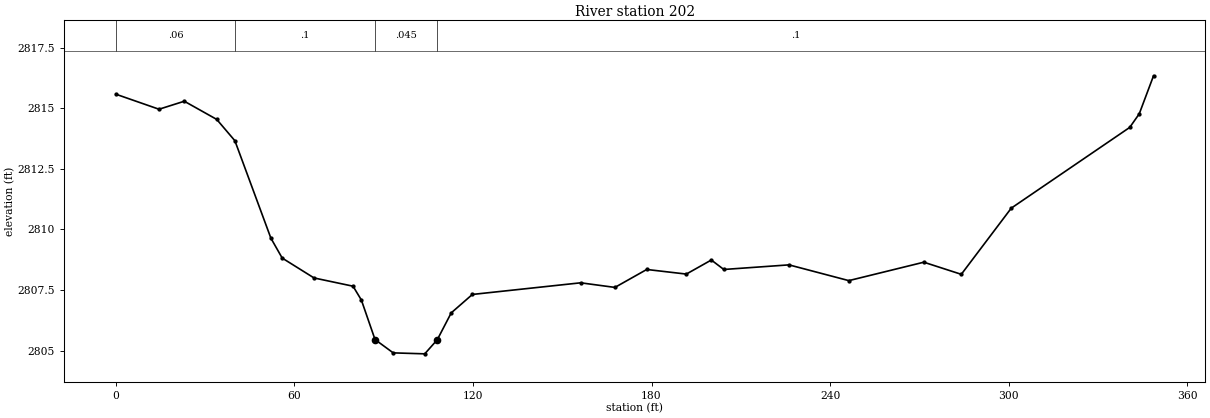
Type RM Length L Ch R = 1 ,202     ,,,
XS GIS Cut Line= 3
2339586.15081562668370.7970907922339722.86346244668490.829807723
2339881.66722015668541.713723752
#Sta/Elev= 30
       0 2815.58    14.5 2814.96      23 2815.29    33.9 2814.54      40 2813.66
    52.1 2809.64    55.9 2808.82    66.6    2808    79.7 2807.66    82.5 2807.09
   87.09 2805.46    93.2 2804.91   103.8 2804.87     108 2805.45   112.7 2806.56
   119.8 2807.32   156.2  2807.8   167.7 2807.61   178.4 2808.35   191.7 2808.16
   200.1 2808.74   204.3 2808.35   226.2 2808.54   246.3 2807.89   271.5 2808.65
   284.1 2808.15   300.9 2810.88   340.7 2814.21   343.9 2814.77   348.7 2816.34
#Mann= 4 ,-1,0
       0     .06       0      40      .1       0   87.09    .045       0
     108      .1       0
Bank Sta=87.09,108
XS Rating Curve= 0 ,0
Exp/Cntr(USF)=0,0
Exp/Cntr=0.3,0.1
LCMann Table=0

Chan Stop Cuts=-1
Use User Specified Reach Order=0
Composite Channel Slope=5